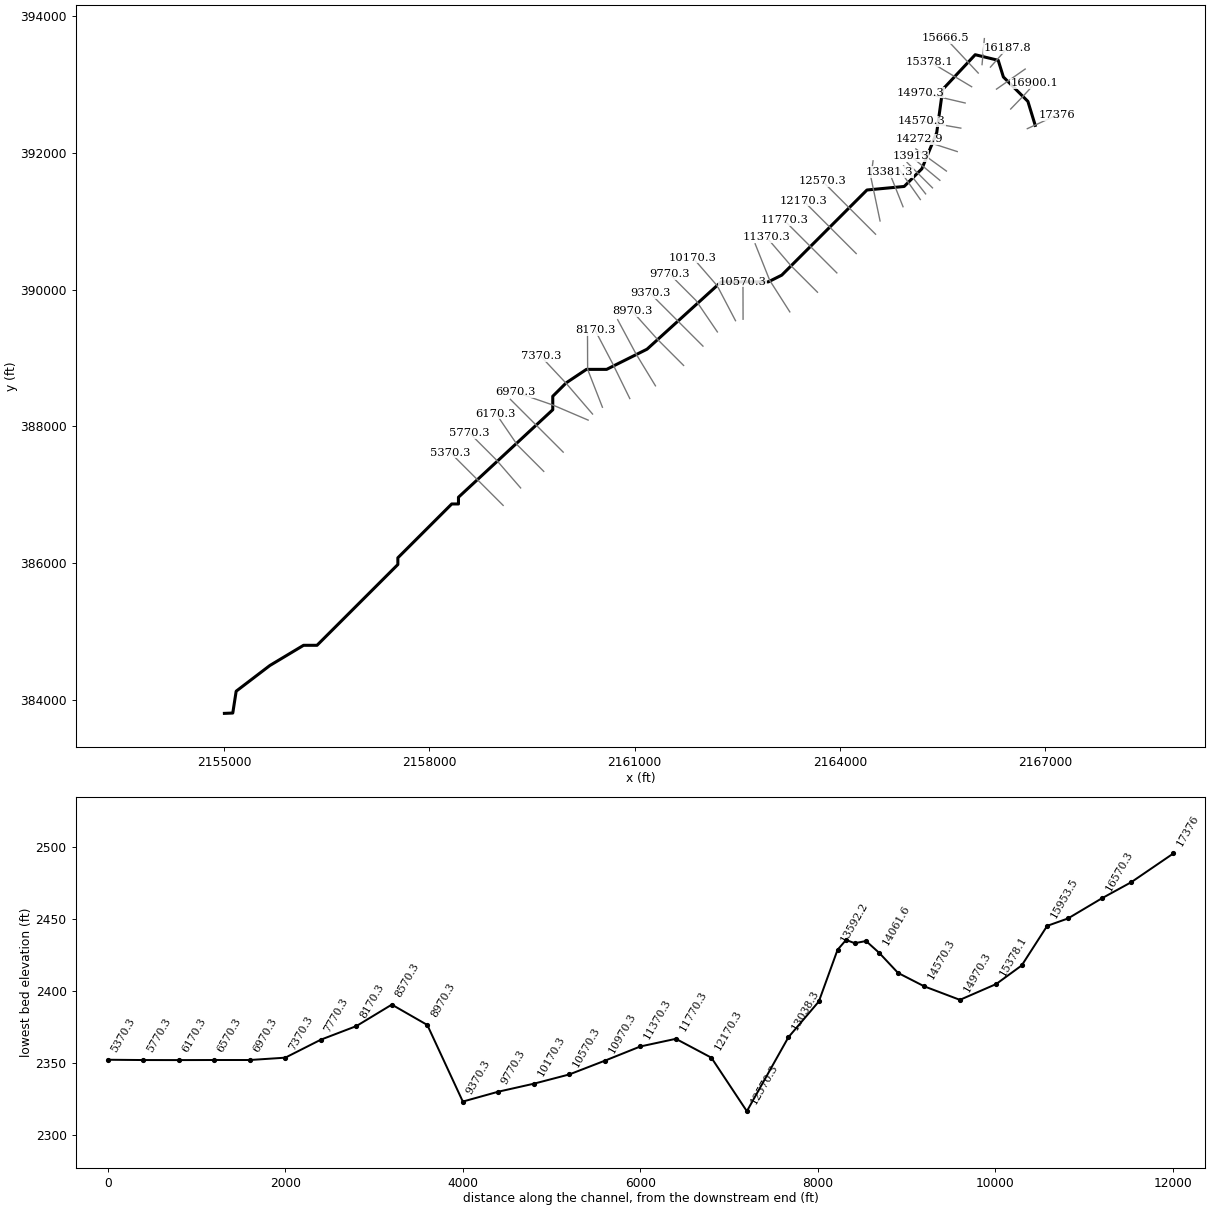
--- SpringCkT4.prj (project) ---

Proj Title=SpringCkT4
Current Plan=p01
Default Exp/Contr=0,0
English Units
Geom File=g01
Flow File=f01
Plan File=p01
BEGIN DESCRIPTION:
END DESCRIPTION:
DSS Export Rating Curves= 0
DSS Export Rating Curve Sorted= 0
DSS Export Volume Flow Curves= 0
DXF OffsetX= 0
DXF OffsetY= 0
DXF ScaleX= 0
DXF ScaleY= 0

--- SpringCkT4.p01 (plan) ---

Plan Title=Floodplain
Program Version=4.00
Geom File=g01
Flow File=f01
K Sum by GR=0
Std Step Tol=0.01
Critical Tol=0.01
Num of Std Step Trials=20
Max Error Tol=0.3
Flow Tol Ratio=0.001
Split Flow NTrial=30
Split Flow Tol=0.02
Split Flow Ratio=0.02
Log Output Level=0
Friction Slope Method=1
Unsteady Friction Slope Method=2
Unsteady Bridges Friction Slope Method=1
Global Log Level=0
CheckData=False
Run HTab=0
Run UNet=0
Run PostProcess=0
UNET Theta=0
UNET Theta Warmup=0
UNET ZTol=0
UNET ZSATol=0
UNET MxIter=0
UNET MaxInSteps=0
UNET DtIC=0
UNET DtMin=0
UNET MaxCRTS=0
UNET WFStab=0
UNET SFStab=0
UNET WFX=0
UNET SFX=0
UNET DSS MLevel=0
UNET DZMax Abort=0
UNET Convert EG Bridges=0
UNET Use Existing IB Tables=0
UNET Froude Limit=0
UNET Froude Power=0
Write IC File=0
Echo Input=False
Echo Output=False
Write Detailed=0

--- SpringCkT4.f01 (steady flow) ---

Flow Title=NFF Regression Equation
Program Version=4.00
Number of Profiles=1
Profile Names=P100yr
River Rch & RM=SpringCkT4,Main      ,17376
4176.328
River Rch & RM=SpringCkT4,Main      ,15666.5
4204.524
River Rch & RM=SpringCkT4,Main      ,13038.3
4222.888
River Rch & RM=SpringCkT4,Main      ,11770.3
4661.496
Boundary for River Rch & Prof#=SpringCkT4,Main      ,1
Up Type=0
Dn Type=3
Dn Slope=0.095966

--- SpringCkT4.g01 (geometry) ---

Geom Title=USGS 10m DEM
Program Version=4.00

River Reach=SpringCkT4      ,Main
Reach XY= 30
     2166855.355      392401.015     2166747.803      392751.927
      2166389.73      393108.697      2166314.21      393352.187
     2165978.272      393434.218     2165503.011      392926.406
     2165415.772      392294.895     2165198.753      391766.044
     2164940.194      391507.484     2164396.396      391455.806
     2163151.155      390210.565     2162954.307      390112.141
     2162265.339      390112.141     2161182.675      389127.901
     2160592.131      388832.629     2160296.859      388832.629
     2160001.587      388635.781     2159804.739      388438.933
     2159804.739      388242.085     2158426.803      386962.573
     2158426.803      386864.149     2158328.379      386864.149
     2157540.987      386076.757     2157540.987      385978.333
     2156359.899      384797.245     2156163.051      384797.245
     2155670.931      384501.973     2155178.272      384126.019
     2155128.696      383806.633     2155006.267       383801.73

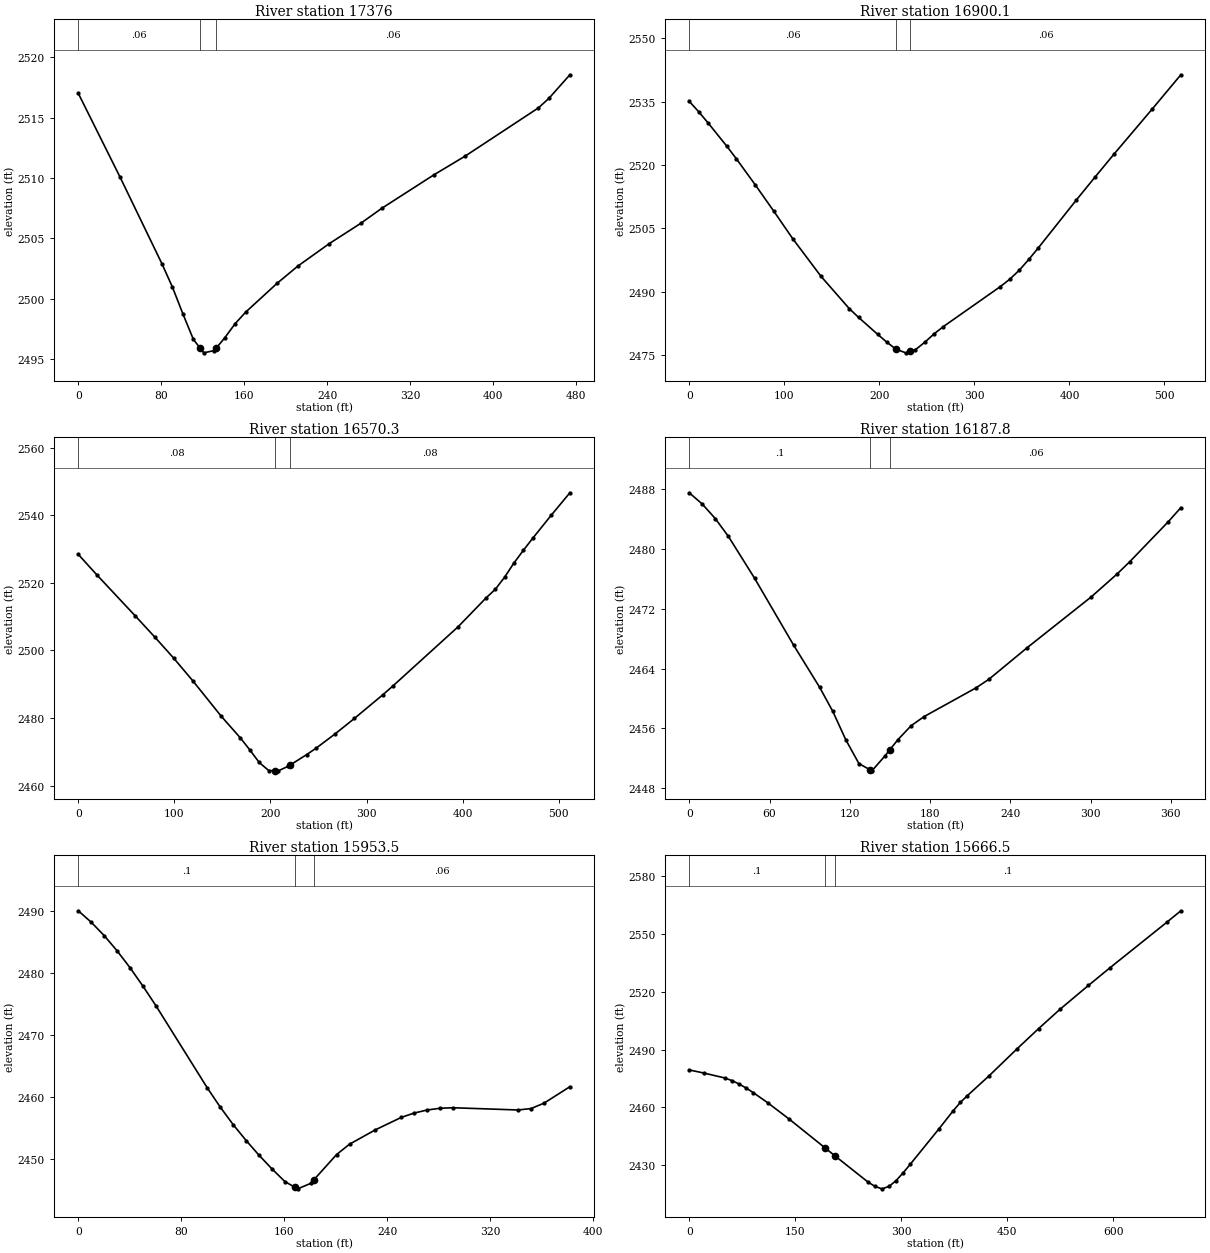
Type RM Length L Ch R = 1 ,17376   ,467.5,475.9,502.8
XS GIS Cut Line= 2
     2166739.677      392352.764      2167170.61       392550.33
#Sta/Elev= 23
       0    2517    40.4 2510.04    80.7 2502.88    90.8 2500.95   100.9 2498.73
     111 2496.62   117.7 2495.88     121 2495.51   131.1  2495.7   132.7 2495.87
   141.2 2496.75   151.3 2497.93   161.4 2498.88   191.6 2501.26   211.8  2502.7
   242.1 2504.56   272.3 2506.23   292.5 2507.47   342.9 2510.25   373.2 2511.81
   443.8  2515.8   453.9 2516.59   474.1 2518.54
#Mann= 3 , 0 , 0
       0     .06       0   117.7    .045       0   132.7     .06       0
Bank Sta=117.7,132.7
XS Rating Curve= 0 ,0
Exp/Cntr=0.3,0.1

Type RM Length L Ch R = 1 ,16900.1 ,335.6,329.8,321.6
XS GIS Cut Line= 3
     2166496.516      392639.924     2166682.542      392831.979
     2166851.117      393016.357
#Sta/Elev= 30
       0  2535.1     9.9 2532.63    19.8 2529.98    39.6 2524.44    49.5  2521.5
    69.3 2515.35    89.1 2509.01   108.9 2502.53   138.6 2493.63   168.4 2485.96
   178.2 2483.88   198.1  2479.9     208 2477.99   217.5 2476.35   227.8 2475.49
   232.5 2475.82   237.7 2476.18   247.6 2477.97   257.5 2479.97   267.4 2481.72
   327.3 2491.19   337.3 2492.95   347.3 2495.09   357.3 2497.64   367.3 2500.38
   407.3 2511.72   427.3 2517.25   447.2 2522.67   487.2  2533.3   517.2 2541.39
#Mann= 3 , 0 , 0
       0     .06       0   217.5    .045       0   232.5     .06       0
Bank Sta=217.5,232.5
XS Rating Curve= 0 ,0
Exp/Cntr=0.3,0.1

Type RM Length L Ch R = 1 ,16570.3 ,376.9,382.5,388.2
XS GIS Cut Line= 3
     2166289.324         392931.     2166565.257       393124.33
     2166708.358      393224.593
#Sta/Elev= 30
       0 2528.39    19.8 2522.18    59.5 2510.13    79.3 2504.03    99.1 2497.75
   118.9 2491.08   148.6 2480.56   168.5 2474.15   178.4 2470.58   188.3 2466.82
   198.2 2464.43   204.9 2464.37   208.1 2464.35     218 2465.64   219.9 2465.97
   237.8 2469.18   247.7  2471.1   267.6 2475.35   287.4 2479.87   317.1  2486.9
     327 2489.36   395.2 2506.96   424.3  2515.5     434 2518.08   443.7 2521.66
   453.4 2525.86   463.1 2529.57   472.8 2533.13   492.2 2539.99   511.6 2546.63
#Mann= 3 , 0 , 0
       0     .08       0   204.9    .045       0   219.9     .08       0
Bank Sta=204.9,219.9
XS Rating Curve= 0 ,0
Exp/Cntr=0.3,0.1

Type RM Length L Ch R = 1 ,16187.8 ,218.2,234.3,250.2
XS GIS Cut Line= 3
     2166200.471      393252.899     2166336.425      393406.018
     2166444.434      393527.663
#Sta/Elev= 25
       0  2487.5     9.8 2485.98    19.5 2484.04    29.2 2481.68    48.8 2476.08
      78 2467.13    97.5 2461.48   107.3 2458.27     117 2454.48   126.8  2451.3
     135 2450.48   136.5 2450.33   146.3 2452.33     150 2453.17     156 2454.51
   165.8 2456.36   175.5 2457.58   214.3 2461.42   223.9 2462.56   252.6  2466.8
   300.5 2473.59   319.6 2476.62   329.2 2478.28   357.9 2483.61   367.4 2485.51
#Mann= 3 , 0 , 0
       0      .1       0     135    .045       0     150     .06       0
Bank Sta=135,150
XS Rating Curve= 0 ,0
Exp/Cntr=0.3,0.1

Type RM Length L Ch R = 1 ,15953.5 ,267.1,287,306.8
XS GIS Cut Line= 3
     2166078.128      393289.342     2166095.003      393479.136
     2166111.948      393669.725
#Sta/Elev= 30
       0 2490.04      10  2488.2    20.1 2486.04    30.1 2483.59    40.1 2480.88
    50.1 2477.92    60.2 2474.76   100.3 2461.44   110.3 2458.37   120.3 2455.55
   130.4 2452.98   140.4 2450.61   150.4 2448.42   160.5 2446.36   168.1 2445.47
   170.5 2445.19   180.5 2446.07   183.1 2446.67   200.6 2450.71   210.7 2452.39
   230.8 2454.71     251 2456.72     261 2457.42   271.1 2457.91   281.2 2458.19
   291.2 2458.27   341.6 2457.91   351.7 2458.14   361.7    2459   381.9 2461.66
#Mann= 3 , 0 , 0
       0      .1       0   168.1    .045       0   183.1     .06       0
Bank Sta=168.1,183.1
XS Rating Curve= 0 ,0
Exp/Cntr=0.3,0.1

Type RM Length L Ch R = 1 ,15666.5 ,280.7,288.4,295.6
XS GIS Cut Line= 3
      2166022.44      393166.072     2165774.031      393431.296
     2165546.982      393673.713
#Sta/Elev= 30
       0 2479.41    20.2 2477.84    50.5 2475.23    60.6 2473.84    70.7 2472.07
    80.8 2469.94    90.8 2467.58     111 2462.38   141.3 2453.92   191.9 2439.02
   206.9 2434.59   252.4 2421.37   262.4 2419.02   272.5  2417.7   282.6 2418.95
   292.7    2422   302.8 2426.09   312.9 2430.56   353.3 2448.84   373.4  2458.2
   383.5 2462.53   393.6 2466.11   423.8 2476.22     464 2490.45   494.2 2500.84
   524.4 2510.84   564.7 2523.26   594.9 2532.33   675.4 2555.98   695.5 2562.02
#Mann= 3 , 0 , 0
       0      .1       0   191.9    .045       0   206.9      .1       0
Bank Sta=191.9,206.9
XS Rating Curve= 0 ,0
Exp/Cntr=0.3,0.1

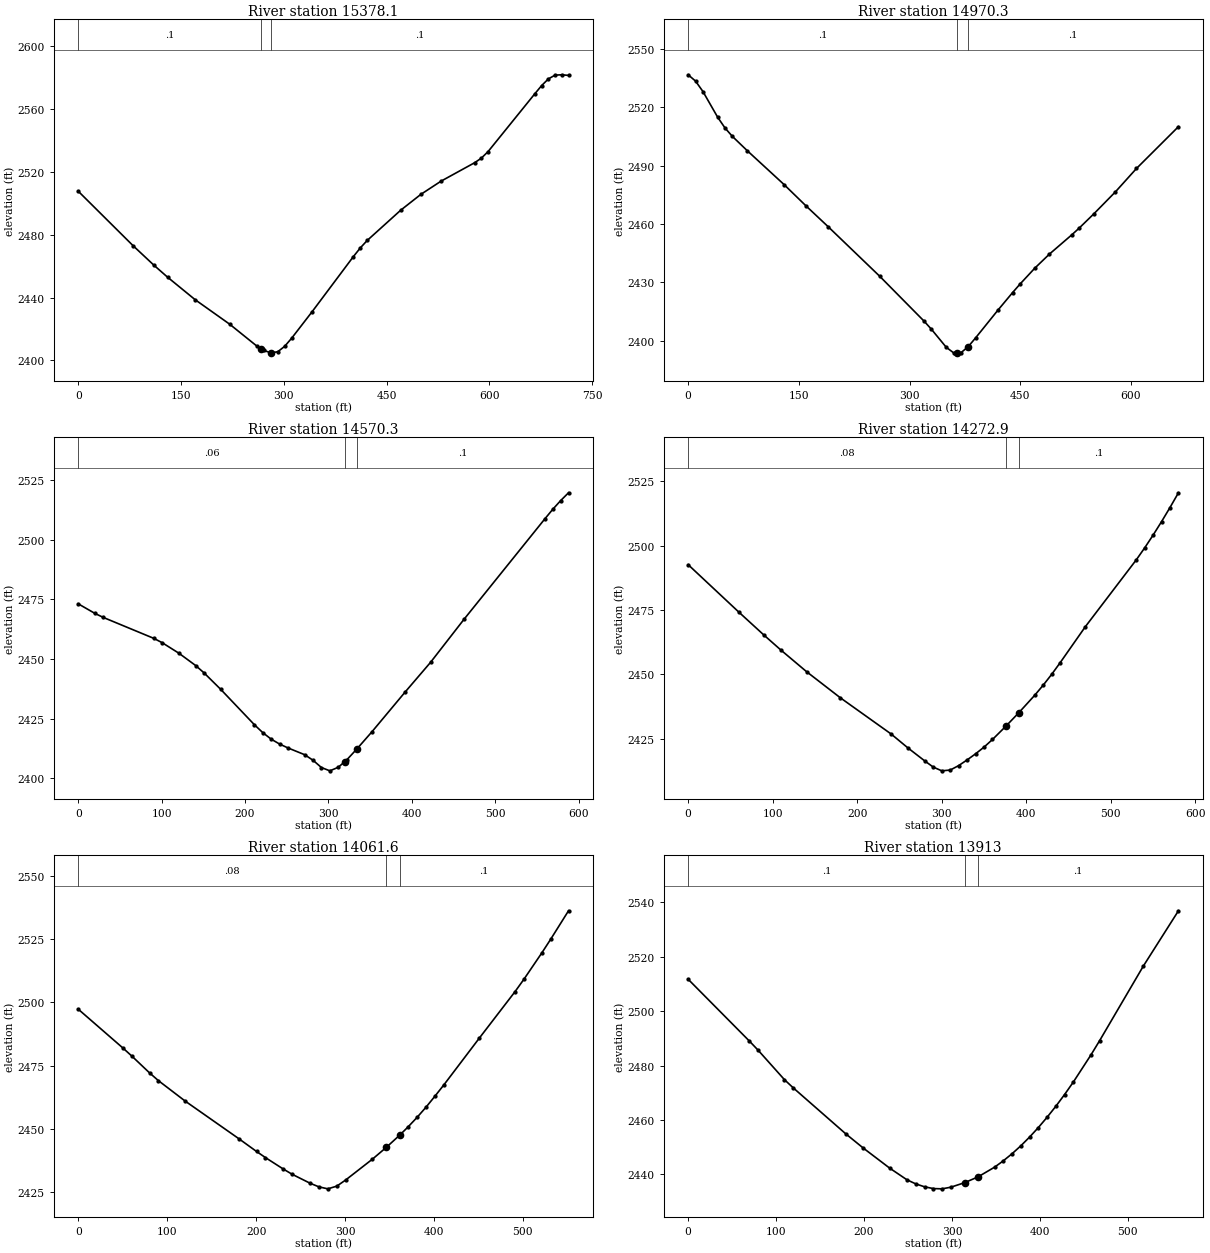
Type RM Length L Ch R = 1 ,15378.1 ,400.5,407.8,411.1
XS GIS Cut Line= 3
     2165926.073      392965.985     2165564.282      393182.695
     2165312.164      393333.711
#Sta/Elev= 30
       0 2507.68    80.3 2472.88   110.4 2460.59   130.5  2452.9   170.7 2438.58
   220.9 2423.04   261.1 2408.92   266.9 2407.37   271.1 2406.25   281.2 2404.76
   281.9 2404.81   291.2 2405.46   301.2 2408.87   311.3 2413.98   341.4 2430.98
   401.6 2466.06   411.7 2471.58   421.7 2476.31   470.7 2495.61   500.1 2505.69
   529.5 2514.08   578.5 2525.82   588.3 2528.72   598.1 2532.88   666.6 2569.85
   676.4 2574.98   686.2 2579.22     696 2581.63   705.8 2581.84   715.6 2581.45
#Mann= 3 , 0 , 0
       0      .1       0   266.9    .045       0   281.9      .1       0
Bank Sta=266.9,281.9
XS Rating Curve= 0 ,0
Exp/Cntr=0.3,0.1

Type RM Length L Ch R = 1 ,14970.3 ,399.1,400,401.2
XS GIS Cut Line= 3
     2165831.263      392728.133     2165276.522      392857.481
     2165184.086      392879.034
#Sta/Elev= 30
       0 2536.76      10 2533.52      20 2528.16      40 2514.93      50 2509.37
      60 2505.06      80 2497.77   129.9 2480.35   159.9 2469.29   189.9  2458.6
   259.8 2433.11   319.8 2410.08   329.8 2405.89   349.8 2396.66   359.8 2393.81
   364.4 2393.85   369.8  2393.9   379.4 2396.93   389.7 2401.56   419.7  2415.7
   439.7 2424.78   449.7 2429.13   469.7  2437.3   489.7  2444.6   519.6 2454.36
   529.6 2457.81   549.6 2465.18   579.1 2476.58   607.6 2488.58   664.5 2510.09
#Mann= 3 , 0 , 0
       0      .1       0   364.4    .045       0   379.4      .1       0
Bank Sta=364.4,379.4
XS Rating Curve= 0 ,0
Exp/Cntr=0.3,0.1

Type RM Length L Ch R = 1 ,14570.3 ,300.6,297.4,294.2
XS GIS Cut Line= 3
     2165767.635      392360.737     2165272.293      392447.247
     2165188.503       392461.88
#Sta/Elev= 30
       0 2473.12    20.1 2469.09    30.2  2467.4    90.5 2458.67   100.6 2456.85
   120.7 2452.43   140.8 2447.27   150.8 2444.21     171 2437.24   211.2 2422.48
   221.2 2419.18   231.3 2416.44   241.4 2414.38   251.4 2412.76   271.5 2409.91
   281.6 2407.57   291.6 2404.54   301.7 2403.15   311.8 2404.65   319.5 2406.97
   321.8 2407.67   334.5 2412.47     352 2419.44   392.2 2436.26   422.4 2448.58
   462.6 2466.65   559.6 2508.76     569 2512.72   578.4 2516.35   587.9 2519.65
#Mann= 3 , 0 , 0
       0     .06       0   319.5    .045       0   334.5      .1       0
Bank Sta=319.5,334.5
XS Rating Curve= 0 ,0
Exp/Cntr=0.3,0.1

Type RM Length L Ch R = 1 ,14272.9 ,218.5,211.3,204.1
XS GIS Cut Line= 2
     2165715.541      392017.754     2165163.547      392196.734
#Sta/Elev= 30
       0 2492.56      60 2474.14      90 2465.14     110 2459.35   140.1 2451.04
   180.1 2440.89   240.1 2426.86   260.1 2421.43   280.1 2416.36   290.1 2413.98
   300.2 2412.53   310.2 2412.84   320.2 2414.57   330.2 2416.78   340.2 2419.14
   350.2 2421.74   360.2  2424.7   376.1 2429.88   391.1    2435   410.2 2441.87
   420.2 2445.78   430.2 2449.96   440.2 2454.47   470.2 2468.53   530.3  2494.4
   540.3 2499.07   550.3 2504.04   560.3 2509.27   570.3 2514.75   580.3 2520.47
#Mann= 3 , 0 , 0
       0     .08       0   376.1    .045       0   391.1      .1       0
Bank Sta=376.1,391.1
XS Rating Curve= 0 ,0
Exp/Cntr=0.3,0.1

Type RM Length L Ch R = 1 ,14061.6 ,150.2,148.6,147
XS GIS Cut Line= 2
     2165557.086      391732.817      2165110.58      392056.408
#Sta/Elev= 30
       0 2497.33    50.1 2482.05    60.2 2478.85    80.2 2472.19    90.2 2469.12
   120.3 2461.05   180.5 2446.24   200.5 2441.18   210.6 2438.74   230.6 2434.24
   240.6 2432.16   260.7 2428.64   270.7  2427.2   280.7 2426.42   290.8 2427.49
   300.8 2429.92   330.9 2438.15   346.6 2442.83   361.6 2447.64     371 2450.89
     381  2454.6     391  2458.6     401 2462.92   411.1 2467.41   451.2 2485.97
   491.3 2504.29   501.3 2509.18   521.4 2519.57   531.4 2524.98   551.4 2536.18
#Mann= 3 , 0 , 0
       0     .08       0   346.6    .045       0   361.6      .1       0
Bank Sta=346.6,361.6
XS Rating Curve= 0 ,0
Exp/Cntr=0.3,0.1

Type RM Length L Ch R = 1 ,13913   ,129.7,127.7,125.7
XS GIS Cut Line= 2
     2165461.765       391597.36     2165032.818      391953.561
#Sta/Elev= 30
       0 2511.73    69.7 2488.98    79.6 2485.63   109.5 2474.81   119.5  2471.8
   179.2  2454.9   199.1 2449.67     229 2442.32   248.9 2437.97   258.9 2436.48
   268.8 2435.41   278.8 2434.76   288.7 2434.66   298.7 2435.26   314.6 2436.95
   329.6 2439.05   348.5 2442.63   358.4 2444.96   368.4 2447.58   378.3 2450.47
   388.3  2453.7   398.3 2457.21   408.2 2460.98   418.2 2465.04   428.1 2469.34
   438.1 2473.96     458 2483.86     468 2489.18   517.7  2516.6   557.6 2536.92
#Mann= 3 , 0 , 0
       0      .1       0   314.6    .045       0   329.6      .1       0
Bank Sta=314.6,329.6
XS Rating Curve= 0 ,0
Exp/Cntr=0.3,0.1

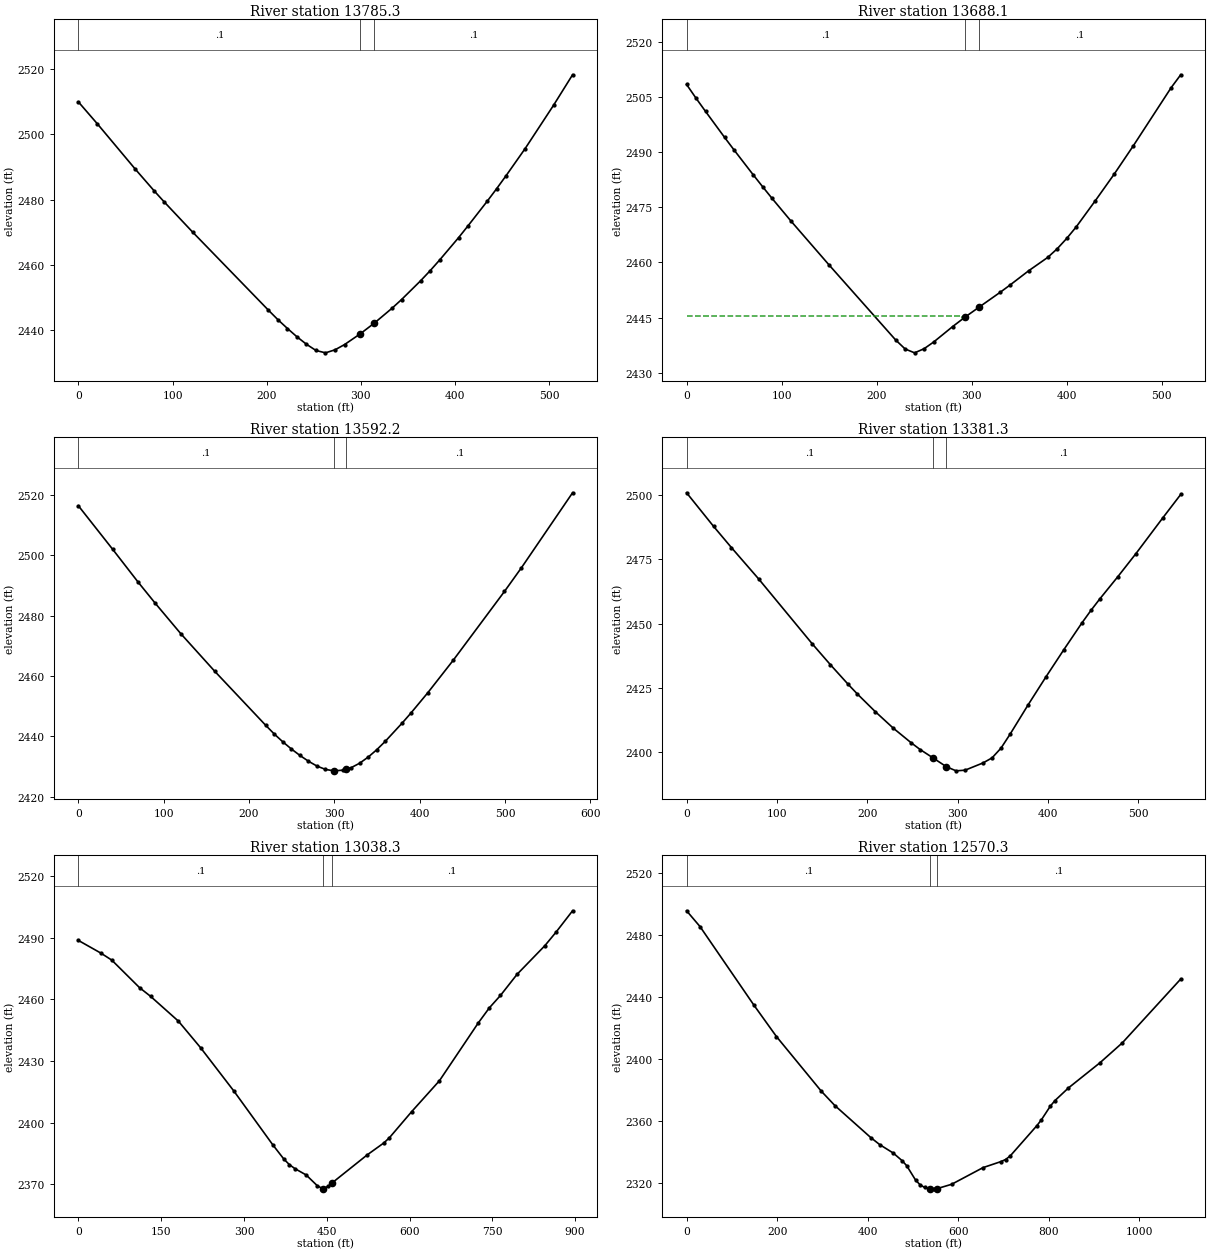
Type RM Length L Ch R = 1 ,13785.3 ,99.9,97.2,94.5
XS GIS Cut Line= 2
     2165353.901      391486.988     2164982.649       391858.24
#Sta/Elev= 30
       0 2509.87    20.2 2503.15    60.6 2489.26    80.8 2482.58    90.9 2479.38
   121.2 2470.12   201.9 2446.19     212 2443.28   222.1  2440.6   232.2 2438.06
   242.3 2435.78   252.4 2433.88   262.5 2433.16   272.6 2434.08   282.7 2435.68
   299.5 2438.99   314.5 2442.28   333.2  2446.8   343.3 2449.45   363.5 2455.18
   373.6 2458.25   383.7 2461.52   403.9 2468.38     414 2472.02   434.2 2479.47
   444.3 2483.34   454.4 2487.34   474.6 2495.61   504.8 2508.86     525 2518.18
#Mann= 3 , 0 , 0
       0      .1       0   299.5    .045       0   314.5      .1       0
Bank Sta=299.5,314.5
XS Rating Curve= 0 ,0
Exp/Cntr=0.3,0.1

Type RM Length L Ch R = 1 ,13688.1 ,97.2,96,94.7
XS GIS Cut Line= 2
     2165253.562      391399.192      2164932.48      391808.071
#Sta/Elev= 30
       0 2508.38      10 2504.63      20 2501.04      40 2493.99      50 2490.56
      70 2483.86      80 2480.59      90 2477.39     110  2471.2     150 2459.29
     220 2438.91     230 2436.46   239.9 2435.42   249.9 2436.54   259.9 2438.35
   279.9 2442.55   292.8  2445.1   307.8 2447.85   329.9 2451.87   339.9 2453.77
   359.9 2457.73   379.9 2461.35   389.9  2463.7   399.9 2466.51   409.9 2469.64
   429.9 2476.73   449.9    2484   469.9 2491.66   509.9 2507.54   519.9 2511.02
#Mann= 3 , 0 , 0
       0      .1       0   292.8    .045       0   307.8      .1       0
#XS Ineff= 2 , 0
          290.17 2445.51
Permanent Ineff=
       F       F
Bank Sta=292.8,307.8
XS Rating Curve= 0 ,0
Exp/Cntr=0.3,0.1

Type RM Length L Ch R = 1 ,13592.2 ,216.4,210.9,205.5
XS GIS Cut Line= 2
     2165176.314      391316.502     2164843.662      391790.707
#Sta/Elev= 30
       0 2516.39      40 2502.04    69.9 2491.14    89.9 2484.16   119.8 2474.09
   159.8 2461.57   219.7 2443.62   229.7 2440.75   239.7 2438.17   249.7 2435.81
   259.7 2433.68   269.6 2431.78   279.6 2430.17   289.6 2429.06   299.1 2428.61
   299.6 2428.59   309.6  2428.8   314.1 2429.17   319.6 2429.63   329.6 2431.11
   339.6 2433.14   349.6 2435.56   359.5 2438.32   379.5 2444.43   389.5 2447.66
   409.5 2454.46   439.4 2465.26   499.4 2488.04   519.3 2495.89   579.2 2520.72
#Mann= 3 , 0 , 0
       0      .1       0   299.1    .045       0   314.1      .1       0
Bank Sta=299.1,314.1
XS Rating Curve= 0 ,0
Exp/Cntr=0.3,0.1

Type RM Length L Ch R = 1 ,13381.3 ,347.1,343,338.8
XS GIS Cut Line= 2
     2164923.408      391211.124     2164721.182       391719.26
#Sta/Elev= 30
       0 2500.97    29.8 2487.92    49.7  2479.6    79.6 2467.49   139.2  2442.1
   159.1 2434.05     179 2426.32   188.9 2422.66   208.8 2415.76   228.7 2409.33
   248.6 2403.61   258.5 2400.99   272.5 2397.79   287.5  2394.3   298.3 2392.69
   308.2 2392.94   328.1 2395.77   338.1 2397.74     348 2401.53     358 2406.93
   377.9 2418.33   397.7 2429.26   417.6  2439.9   437.5 2450.26   447.5 2455.14
   457.4 2459.66   477.3 2468.29   497.2 2477.22     527 2491.17   546.9 2500.31
#Mann= 3 , 0 , 0
       0      .1       0   272.5    .045       0   287.5      .1       0
Bank Sta=272.5,287.5
XS Rating Curve= 0 ,0
Exp/Cntr=0.3,0.1

Type RM Length L Ch R = 1 ,13038.3 ,453.4,467.9,482.3
XS GIS Cut Line= 3
     2164587.779      391003.207     2164453.311        391643.3
     2164485.418      391882.366
#Sta/Elev= 30
       0  2488.6    40.2 2482.52    60.4 2479.05   110.7 2465.66   130.8 2461.41
   181.1 2449.38   221.4 2436.43   281.8 2415.33   352.2 2389.22   372.3 2382.28
   382.4 2379.56   392.4 2377.64   412.6 2374.59   432.7 2369.38   442.8 2367.84
   443.6 2367.95   452.8 2369.14   458.6 2370.51   523.2 2384.34   553.4 2390.17
   563.5  2392.7   603.8 2405.38   654.1  2420.4   724.4 2448.48   744.5 2455.83
   764.6 2461.84   794.8 2472.15     845 2486.03   865.1 2492.55   895.3 2503.03
#Mann= 3 , 0 , 0
       0      .1       0   443.6    .045       0   458.6      .1       0
Bank Sta=443.6,458.6
XS Rating Curve= 0 ,0
Exp/Cntr=0.3,0.1

Type RM Length L Ch R = 1 ,12570.3 ,400,400,400
XS GIS Cut Line= 3
     2164521.873      390809.123     2164135.792      391195.203
     2163749.712      391581.283
#Sta/Elev= 30
       0 2495.42    29.8 2485.21   148.9 2434.65   198.6 2414.47   297.8 2379.29
   327.6 2370.09     407 2349.47   426.9  2344.9   456.6 2339.52   476.5 2334.54
   486.4 2331.36   506.3 2321.99   516.2 2319.03   526.2 2317.33   538.5 2316.57
     546 2316.46   553.5 2316.59   585.7 2319.38   655.2 2330.13   694.9 2334.01
   704.8 2335.33   714.8  2337.5   774.3 2357.18   784.2 2360.93   804.1 2369.78
     814 2373.24   843.8 2381.38   913.3 2397.54     963 2410.42    1092 2451.48
#Mann= 3 , 0 , 0
       0      .1       0   538.5    .045       0   553.5      .1       0
Bank Sta=538.5,553.5
XS Rating Curve= 0 ,0
Exp/Cntr=0.3,0.1

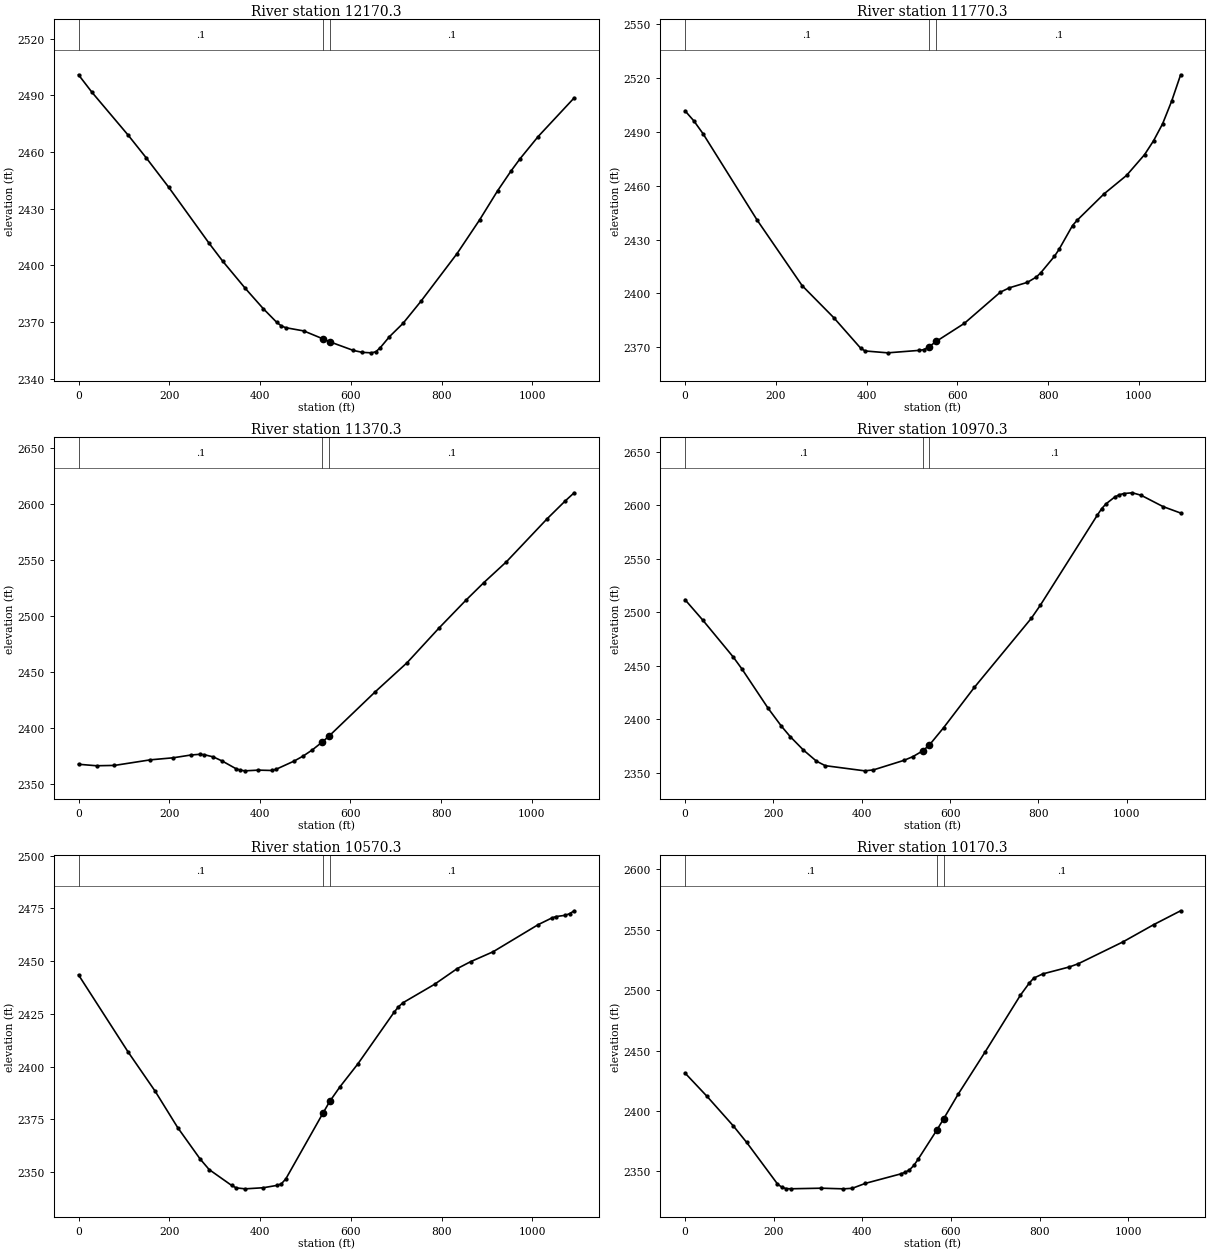
Type RM Length L Ch R = 1 ,12170.3 ,400,400,400
XS GIS Cut Line= 3
      2164239.03       390526.28      2163852.95       390912.36
     2163466.869      391298.441
#Sta/Elev= 30
       0 2500.95    29.8 2491.63   109.2 2469.02   148.9 2457.04   198.6 2441.41
   287.9 2411.63   317.7  2402.2   367.3 2387.84     407 2377.06   436.8 2369.79
   446.7 2367.94   456.6 2366.97   496.4 2365.25   538.5 2361.06   553.5 2359.51
   605.6 2354.92   625.4  2353.9   645.3 2353.65   655.2 2354.24   665.1 2356.46
     685  2362.2   714.8 2369.23   754.5 2380.99   833.9 2406.21   883.5 2424.02
   923.2 2439.46     953 2450.02   972.9 2456.51  1012.6 2468.22    1092 2488.71
#Mann= 3 , 0 , 0
       0      .1       0   538.5    .045       0   553.5      .1       0
Bank Sta=538.5,553.5
XS Rating Curve= 0 ,0
Exp/Cntr=0.3,0.1

Type RM Length L Ch R = 1 ,11770.3 ,400,400,398.3
XS GIS Cut Line= 3
     2163956.187      390243.437     2163570.107      390629.517
     2163184.027      391015.598
#Sta/Elev= 30
       0 2501.86    19.8 2496.13    39.7 2489.07   158.8  2440.9   258.1 2404.26
   327.6 2386.43   387.2  2369.3   397.1 2367.79   446.7 2366.75   516.2 2368.13
   526.2 2368.54   538.5 2370.27   553.5 2373.13   615.5  2383.2   694.9 2400.63
   714.8 2403.05   754.5  2406.1   774.3 2409.09   784.2 2411.53     814 2420.63
     824 2424.44   853.8 2437.79   863.7 2440.67   923.2 2455.45   972.9 2465.78
  1012.6 2477.38  1032.4 2485.13  1052.3 2494.59  1072.2 2507.21    1092 2521.93
#Mann= 3 , 0 , 0
       0      .1       0   538.5    .045       0   553.5      .1       0
Bank Sta=538.5,553.5
XS Rating Curve= 0 ,0
Exp/Cntr=0.3,0.1

Type RM Length L Ch R = 1 ,11370.3 ,405,400,392
XS GIS Cut Line= 3
       2163673.1      389960.839     2163287.264      390346.675
     2162930.649      390762.707
#Sta/Elev= 30
       0 2367.32    39.7 2365.99    79.4 2366.29   158.7 2371.29   208.3 2373.08
     248 2375.59   267.9 2376.24   277.8 2375.84   297.6 2373.87   317.5 2370.12
   347.2 2363.41   357.2 2362.01   367.1 2361.44   396.8 2362.07   426.6 2361.76
   436.5 2362.94   476.2 2370.27     496 2374.76   515.9 2380.17   538.2 2387.34
   553.2  2392.7   655.2 2432.31     725 2458.16   794.7 2488.84   854.5 2513.91
   894.4  2529.8   944.2 2548.41  1033.8 2586.78  1073.7 2602.72  1093.6 2610.08
#Mann= 3 , 0 , 0
       0      .1       0   538.2    .045       0   553.2      .1       0
Bank Sta=538.2,553.2
XS Rating Curve= 0 ,0
Exp/Cntr=0.3,0.1

Type RM Length L Ch R = 1 ,10970.3 ,413.6,400,391
XS GIS Cut Line= 3
      2163268.85      389673.387     2162975.594      390133.428
     2162762.389      390668.807
#Sta/Elev= 30
       0 2511.61    39.7 2492.76   109.1 2458.04     129 2446.75   188.5 2409.86
   218.2 2393.34   238.1  2383.6   267.8  2371.1   297.6 2360.59   317.4  2356.4
   406.7 2351.56   426.5 2352.44     496 2361.42   515.8 2364.84   538.1 2370.22
   553.1 2375.69   585.3 2391.86   654.8 2429.51     784 2494.24   803.9 2506.16
     933 2590.44     943 2596.61   952.9 2601.15   972.8 2607.58   982.7 2609.56
   992.7 2610.77  1012.5  2611.5  1032.4 2609.17  1082.1 2598.57  1121.8 2592.55
#Mann= 3 , 0 , 0
       0      .1       0   538.1    .045       0   553.1      .1       0
Bank Sta=538.1,553.1
XS Rating Curve= 0 ,0
Exp/Cntr=0.3,0.1

Type RM Length L Ch R = 1 ,10570.3 ,388.5,400,417.1
XS GIS Cut Line= 2
     2162585.874      389566.141     2162584.411      390112.141
#Sta/Elev= 30
       0 2443.49   109.2 2406.95   168.8 2388.34   218.4  2371.1     268 2356.15
   287.9 2351.15   337.5 2343.62   347.5 2342.47   367.3 2342.02     407 2342.54
   436.8 2343.64   446.7 2344.36   456.7 2346.73   538.5 2377.89   553.5  2383.5
   575.8 2390.35   615.5 2401.29   694.9 2425.66   704.8 2428.33   714.8 2430.27
   784.3 2439.01   833.9 2446.41   863.7 2449.74   913.3 2454.44  1012.6  2467.3
  1042.4 2470.44  1052.3 2471.16  1072.2 2471.74  1082.1 2472.53    1092 2473.89
#Mann= 3 , 0 , 0
       0      .1       0   538.5    .045       0   553.5      .1       0
Bank Sta=538.5,553.5
XS Rating Curve= 0 ,0
Exp/Cntr=0.3,0.1

Type RM Length L Ch R = 1 ,10170.3 ,397.2,400,401.6
XS GIS Cut Line= 3
     2162475.343       389544.47     2162208.114      390054.917
     2161852.597      390464.388
#Sta/Elev= 30
       0 2431.47    49.7 2412.15   109.3 2387.57   139.1 2374.06   208.6 2339.69
   218.6 2336.84   228.5 2335.76   238.4 2335.63     308 2336.11   357.6 2335.58
   377.5 2336.03   407.3 2340.14   486.8 2347.94   496.7 2349.28   506.6 2351.27
   516.6 2355.02   526.5 2360.33   568.7 2384.45   583.7 2393.58   616.3 2413.85
   676.6 2448.48   756.9 2495.86     777 2505.96     787 2510.01   807.1 2513.44
   867.4 2519.24   887.5  2521.9   987.9  2539.9  1058.2 2554.36  1118.4 2565.72
#Mann= 3 , 0 , 0
       0      .1       0   568.7    .045       0   583.7      .1       0
Bank Sta=568.7,583.7
XS Rating Curve= 0 ,0
Exp/Cntr=0.3,0.1

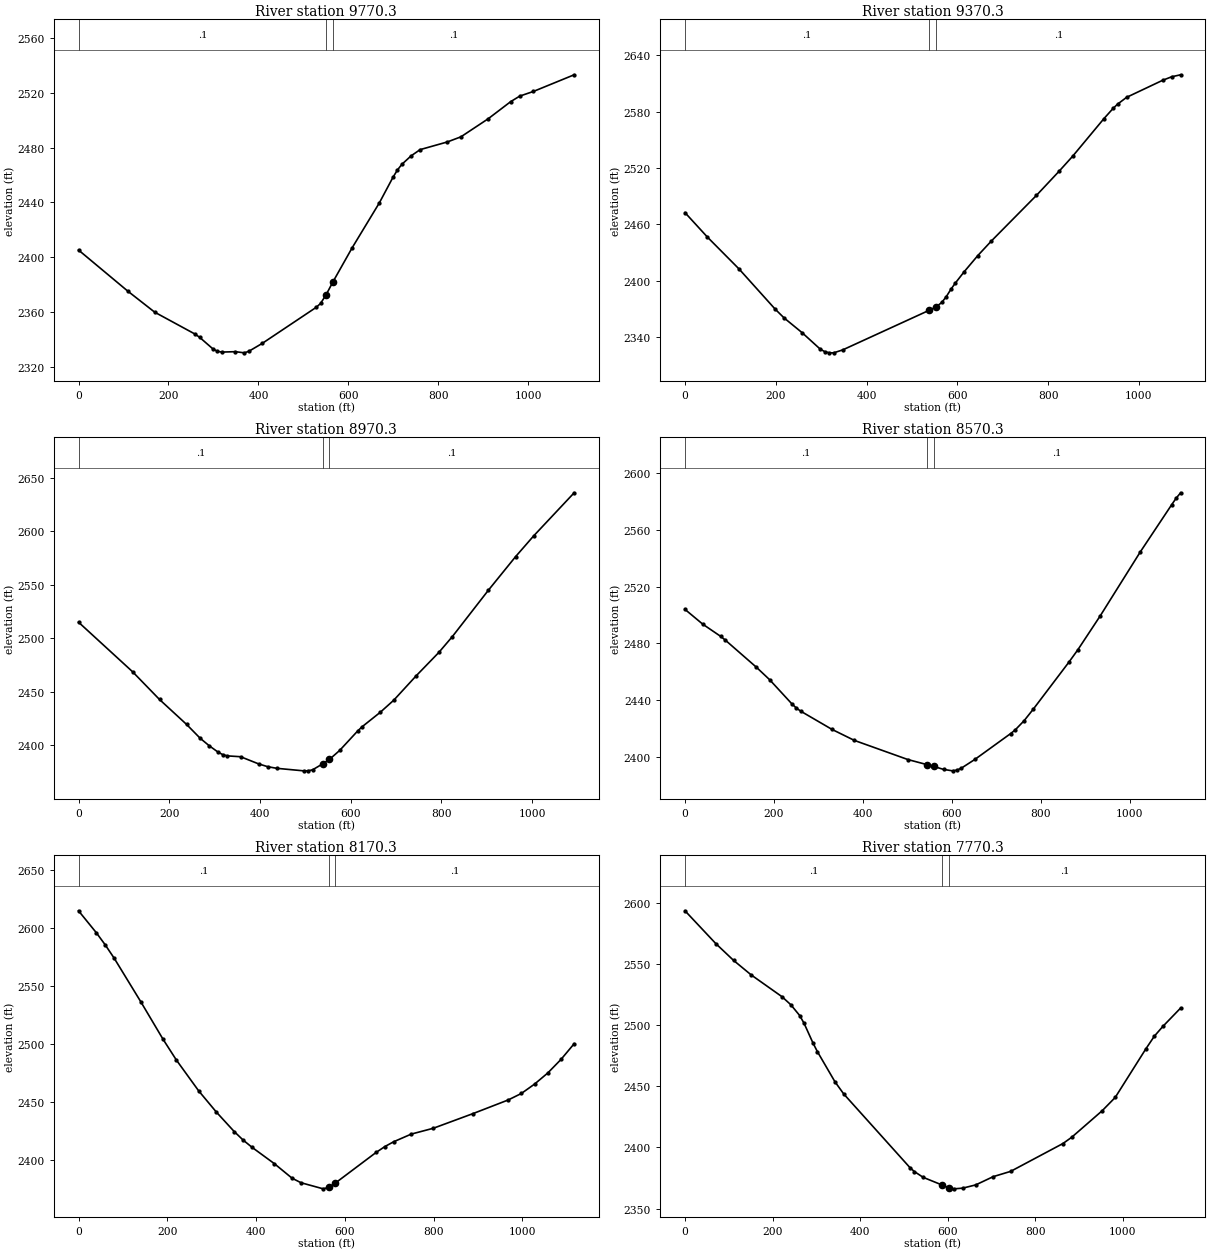
Type RM Length L Ch R = 1 ,9770.3  ,395.7,400,400
XS GIS Cut Line= 3
     2162210.274      389380.426     2161896.444       389841.67
     2161511.847      390226.268
#Sta/Elev= 30
       0 2405.15   109.6 2375.11   169.4 2359.73     259 2343.74     269 2341.43
   298.9 2332.87   308.8 2331.12   318.8 2330.59   348.7 2330.88   368.6 2330.03
   378.6 2331.16   408.4 2336.93     528 2363.19     538  2366.1   550.4 2372.49
   565.4 2381.79   608.2 2406.74   668.7 2439.59   698.9 2458.22     709 2463.67
     719 2467.84   739.2 2473.93   759.3 2478.51   819.8 2484.12     850 2487.86
   910.4    2501   960.8 2513.61   980.9 2517.64  1011.1 2521.02  1101.8 2533.21
#Mann= 3 , 0 , 0
       0      .1       0   550.4    .045       0   565.4      .1       0
Bank Sta=550.4,565.4
XS Rating Curve= 0 ,0
Exp/Cntr=0.3,0.1

Type RM Length L Ch R = 1 ,9370.3  ,400,400,398.8
XS GIS Cut Line= 3
     2161999.682      389172.747     2161613.601      389558.828
     2161227.521      389944.908
#Sta/Elev= 30
       0 2472.48    49.6 2446.32   119.1 2412.48   198.6 2369.75   218.4 2360.32
   258.1 2344.62   297.8 2327.19   307.8 2324.47   317.7 2323.19   327.6 2323.17
   347.4 2326.28   538.5 2368.58   553.5 2372.16   565.8 2376.86   575.8 2383.08
   585.7 2390.69   595.6 2397.44   615.5 2409.74   645.3 2426.81     675 2442.23
   774.3  2490.8     824  2516.4   853.8 2532.33   923.2 2572.65   943.1 2583.35
     953 2587.93   972.9  2595.2  1052.3 2613.35  1072.2  2617.1    1092 2619.23
#Mann= 3 , 0 , 0
       0      .1       0   538.5    .045       0   553.5      .1       0
Bank Sta=538.5,553.5
XS Rating Curve= 0 ,0
Exp/Cntr=0.3,0.1

Type RM Length L Ch R = 1 ,8970.3  ,405.5,400,394.4
XS GIS Cut Line= 3
     2161716.713      388890.031     2161330.759      389275.985
     2160965.867      389683.505
#Sta/Elev= 30
       0 2515.05   119.1 2468.85   178.6 2442.92   238.2  2419.7     268 2406.85
   287.8 2399.89   307.6 2393.84   317.6 2391.57   327.5 2390.33   357.3 2389.53
     397 2382.86   416.8 2380.27   436.7 2378.73   496.2 2376.36   506.1 2376.38
     516 2377.29   538.3 2382.87   553.3 2387.05   575.7 2395.36   615.4 2413.52
   625.4 2417.53   665.2 2430.95     695 2442.24   744.7 2465.12   794.5 2486.85
   824.3 2501.64   903.9 2544.99   963.5 2576.11  1003.3 2595.45  1092.8 2635.77
#Mann= 3 , 0 , 0
       0      .1       0   538.3    .045       0   553.3      .1       0
Bank Sta=538.3,553.3
XS Rating Curve= 0 ,0
Exp/Cntr=0.3,0.1

Type RM Length L Ch R = 1 ,8570.3  ,402.2,400,399.8
XS GIS Cut Line= 3
     2161305.513      388591.953     2161019.088      389062.739
     2160753.228      389558.947
#Sta/Elev= 30
       0 2503.93    40.1 2493.51    80.2 2484.98    90.2 2482.46   160.3 2463.35
   190.4 2454.48   240.5 2437.48   250.5 2434.59   260.5 2432.35   330.6 2419.59
   380.7 2411.89     501 2398.44   543.6  2394.9   558.6 2393.65   581.2 2391.52
   601.3 2390.51   611.4 2391.02   621.4 2392.44   651.6 2398.54     732  2416.7
   742.1 2419.22   762.2 2425.73   782.3 2433.63   862.7 2466.79   882.8 2475.47
   933.1 2499.29  1023.5 2544.39  1093.9 2577.48    1104 2582.08    1114 2585.85
#Mann= 3 , 0 , 0
       0      .1       0   543.6    .045       0   558.6      .1       0
Bank Sta=543.6,558.6
XS Rating Curve= 0 ,0
Exp/Cntr=0.3,0.1

Type RM Length L Ch R = 1 ,8170.3  ,402.2,400,388.5
XS GIS Cut Line= 3
     2160930.426       388406.03      2160678.59      388919.088
     2160425.276      389402.145
#Sta/Elev= 30
       0  2614.6    40.1 2595.76    60.2  2585.3    80.2 2573.94   140.4 2536.36
   190.5 2504.16   220.6 2486.26   270.7 2459.84   310.8 2441.49   350.9 2424.81
     371 2417.49     391 2411.28   441.2 2397.26   481.3 2384.71   501.4 2380.82
   551.5 2375.57     564 2376.93     579  2380.6   670.7 2406.88   690.5 2411.93
   710.4 2416.08     750 2422.64   799.6 2427.65   888.9 2440.23   968.2 2451.95
     998 2457.55  1027.7  2465.6  1057.5 2475.15  1087.2 2486.76    1117 2500.33
#Mann= 3 , 0 , 0
       0      .1       0     564    .045       0     579      .1       0
Bank Sta=564,579
XS Rating Curve= 0 ,0
Exp/Cntr=0.3,0.1

Type RM Length L Ch R = 1 ,7770.3  ,391.2,400,417.8
XS GIS Cut Line= 3
     2160530.381      388279.009     2160314.403      388832.629
     2160312.247      389370.114
#Sta/Elev= 30
       0 2593.58    70.5  2566.7   110.8 2553.05   151.1 2541.14   221.6 2523.28
   241.7 2516.72   261.9 2507.91     272  2501.5   292.1 2485.57   302.2 2478.47
   342.4 2453.75   362.6 2443.71   513.7  2383.5   523.8 2380.28   543.9 2375.54
   586.8 2369.32   601.8 2367.07   614.2 2366.14   634.1  2366.7   663.9 2369.36
   703.8 2376.11   743.6 2380.42     863 2403.19   882.9 2408.27   952.6    2430
   982.4 2440.89  1052.1 2480.48    1072 2491.11  1091.9 2499.26  1131.8 2514.03
#Mann= 3 , 0 , 0
       0      .1       0   586.8    .045       0   601.8      .1       0
Bank Sta=586.8,601.8
XS Rating Curve= 0 ,0
Exp/Cntr=0.3,0.1

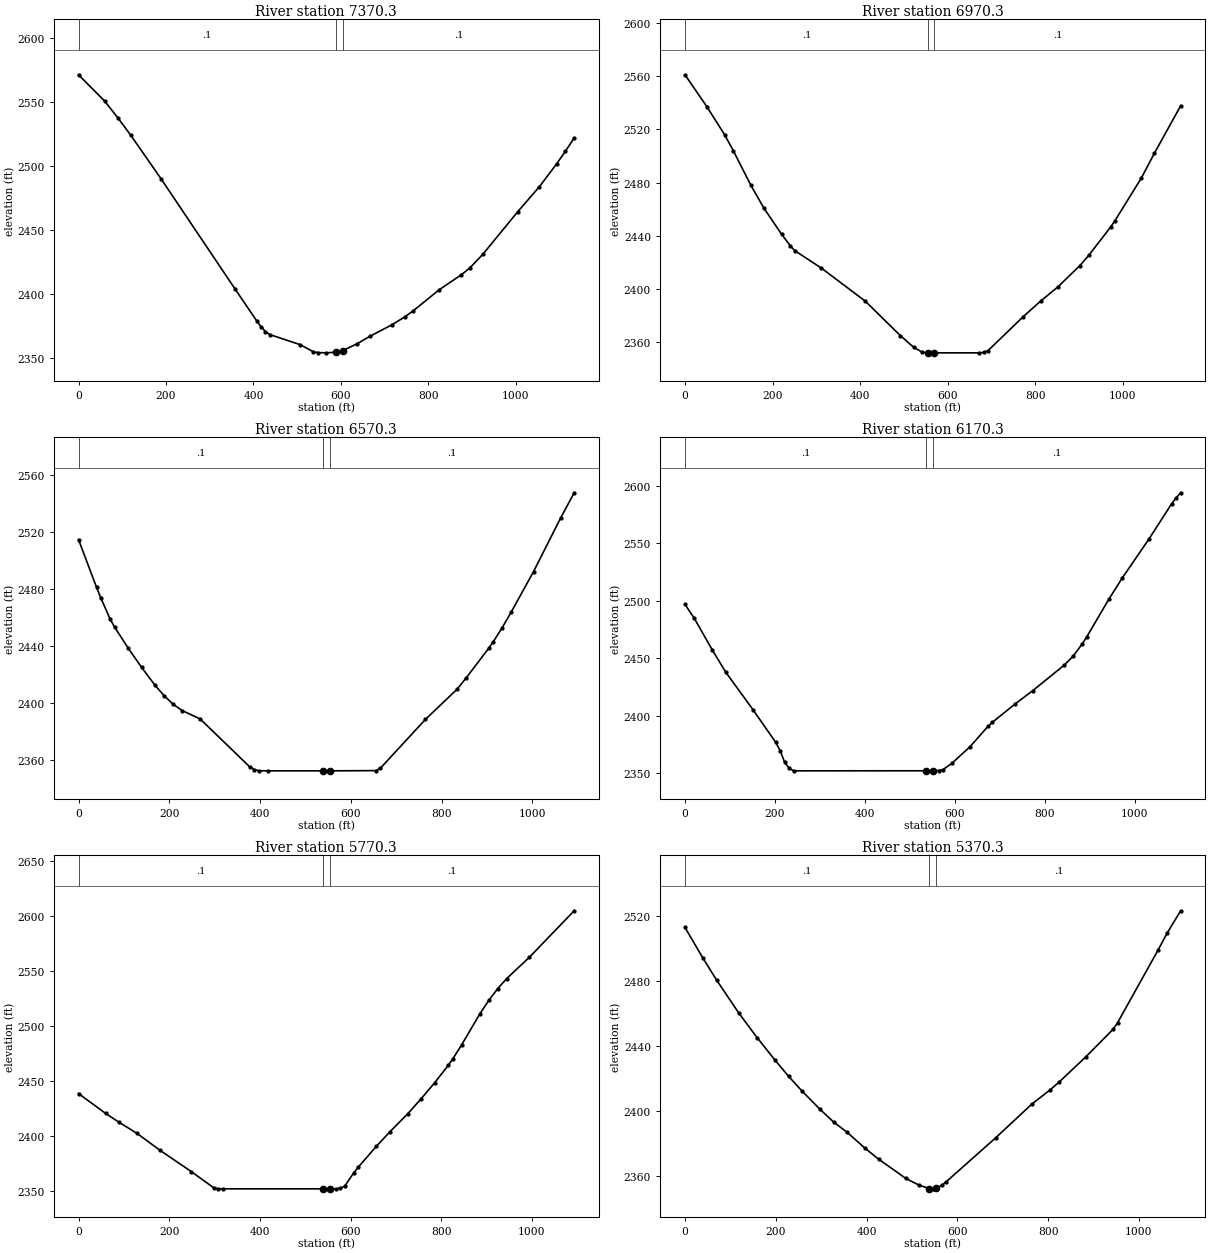
Type RM Length L Ch R = 1 ,7370.3  ,389.9,400,411.6
XS GIS Cut Line= 3
     2160386.255      388179.434     2159997.594      388631.788
     2159630.562      389023.663
#Sta/Elev= 30
       0  2571.2    59.6 2550.69    89.5 2537.71   119.3 2523.98   188.9 2489.73
   357.8 2403.68   407.5 2378.62   417.5 2374.02   427.4 2370.34   437.4 2367.94
   506.9 2360.07   536.8 2354.53   546.7 2353.87   566.6 2353.66   588.9 2354.16
   603.9 2355.44   636.2 2360.62     666 2366.56   715.7 2375.45   745.5 2381.66
   765.4 2386.56   825.1  2403.1   874.8 2414.63   894.7 2420.04   924.5 2430.75
    1004 2463.95  1053.8 2483.63  1093.5 2501.69  1113.4 2511.42  1133.3 2521.79
#Mann= 3 , 0 , 0
       0      .1       0   588.9    .045       0   603.9      .1       0
Bank Sta=588.9,603.9
XS Rating Curve= 0 ,0
Exp/Cntr=0.3,0.1

Type RM Length L Ch R = 1 ,6970.3  ,409,400,389.2
XS GIS Cut Line= 3
      2160321.52      388090.621     2159804.739      388311.671
     2159266.342      388498.198
#Sta/Elev= 30
       0 2561.04    50.2 2536.96    90.3 2516.07   110.4 2503.94   150.6 2477.91
   180.7 2460.53   220.8 2441.12   240.9 2432.34   250.9  2428.8   311.2 2415.81
   411.5 2390.93   491.8 2365.01   521.9  2356.3     542 2352.49   554.6 2352.05
   562.1 2352.03   569.6 2352.03     672 2352.03     682  2352.3     692 2353.68
     772  2379.1     812 2390.87     852 2401.72     902 2417.67   921.9 2425.25
   971.9 2446.52   981.9 2451.36  1041.9 2483.25  1071.9 2502.02  1131.9 2537.68
#Mann= 3 , 0 , 0
       0      .1       0   554.6    .045       0   569.6      .1       0
Bank Sta=554.6,569.6
XS Rating Curve= 0 ,0
Exp/Cntr=0.3,0.1

Type RM Length L Ch R = 1 ,6570.3  ,400,400,395.7
XS GIS Cut Line= 3
     2159957.181      387622.367     2159571.101      388008.447
      2159185.02      388394.527
#Sta/Elev= 30
       0 2514.88    39.7 2481.28    49.6 2473.41    69.5 2459.02    79.4 2453.27
   109.2 2438.55     139 2424.88   168.8 2412.17   188.6 2404.98   208.5 2398.92
   228.3 2394.47     268 2388.57   377.2 2354.83   387.2 2352.97   397.1 2352.09
     417 2352.03   538.5 2352.03   553.5 2352.03   655.2 2352.19   665.1  2353.9
   764.4 2388.28   833.9 2409.46   853.8 2417.35   903.4  2438.2   913.3 2442.67
   933.2 2452.72     953 2463.65  1002.6 2492.38  1062.2 2530.12    1092 2547.82
#Mann= 3 , 0 , 0
       0      .1       0   538.5    .045       0   553.5      .1       0
Bank Sta=538.5,553.5
XS Rating Curve= 0 ,0
Exp/Cntr=0.3,0.1

Type RM Length L Ch R = 1 ,6170.3  ,401.6,400,404.3
XS GIS Cut Line= 3
     2159672.868      387340.995     2159288.258      387725.604
     2158974.128      388186.526
#Sta/Elev= 30
       0 2496.76    20.2  2484.9    60.4 2457.28    90.6 2437.77   151.1 2405.17
   201.4 2376.91   211.5 2369.51   221.6 2359.35   231.7 2354.11   241.7 2351.98
   536.4 2352.03   551.4 2352.03   563.8  2352.2   573.8 2353.11   593.7 2358.68
   633.6 2372.96   673.4 2390.61   683.4 2394.23   733.2 2409.95     773 2421.71
   842.7 2443.77   862.7 2451.66   882.6 2462.17   892.5 2468.13   942.3 2501.28
   972.2  2519.8    1032 2553.94  1081.8 2584.21  1091.8 2589.37  1101.7 2593.73
#Mann= 3 , 0 , 0
       0      .1       0   536.4    .045       0   551.4      .1       0
Bank Sta=536.4,551.4
XS Rating Curve= 0 ,0
Exp/Cntr=0.3,0.1

Type RM Length L Ch R = 1 ,5770.3  ,398.4,400,400
XS GIS Cut Line= 3
     2159335.325      387098.515     2158976.588      387512.358
     2158590.717      387898.228
#Sta/Elev= 30
       0 2438.69    59.8 2420.62    89.6  2412.5   129.4 2402.36   179.2 2387.21
     249 2367.64   298.7 2352.85   308.7 2352.08   318.6 2352.03   540.2 2352.03
   555.2 2352.03   567.5 2352.01   577.4 2352.51   587.4 2354.55   607.2 2366.58
   617.1 2371.72   656.8 2390.58   686.6 2403.74   726.3  2420.3     756 2434.06
   785.8 2448.54   815.6 2464.35   825.5 2470.15   845.3 2483.07     885 2510.88
   904.9 2523.34   924.7 2534.09   944.6 2543.27   994.2 2562.46  1093.4 2604.91
#Mann= 3 , 0 , 0
       0      .1       0   540.2    .045       0   555.2      .1       0
Bank Sta=540.2,555.2
XS Rating Curve= 0 ,0
Exp/Cntr=0.3,0.1

Type RM Length L Ch R = 1 ,5370.3  ,392.2,400,399
XS GIS Cut Line= 3
     2159079.825      386843.435     2158693.745      387229.515
     2158307.665      387615.596
#Sta/Elev= 30
       0 2513.18    39.7  2494.2    69.5 2480.82   119.1 2460.25   158.8 2445.36
   198.6 2431.37   228.3  2421.5   258.1 2412.36   297.8 2401.09   327.6 2393.32
   357.4 2386.98   397.1 2377.11   426.9 2370.43   486.4 2358.64   516.2  2354.4
   538.5 2352.41     546 2352.21   553.5 2352.49   565.8 2354.36   575.8 2356.65
     685 2383.75   764.4 2404.44   804.1 2413.08     824 2417.89   883.5 2433.58
   943.1 2450.44     953 2454.44  1042.4 2499.31  1062.2 2509.64    1092 2523.42
#Mann= 3 , 0 , 0
       0      .1       0   538.5    .045       0   553.5      .1       0
Bank Sta=538.5,553.5
XS Rating Curve= 0 ,0
Exp/Cntr=0.3,0.1