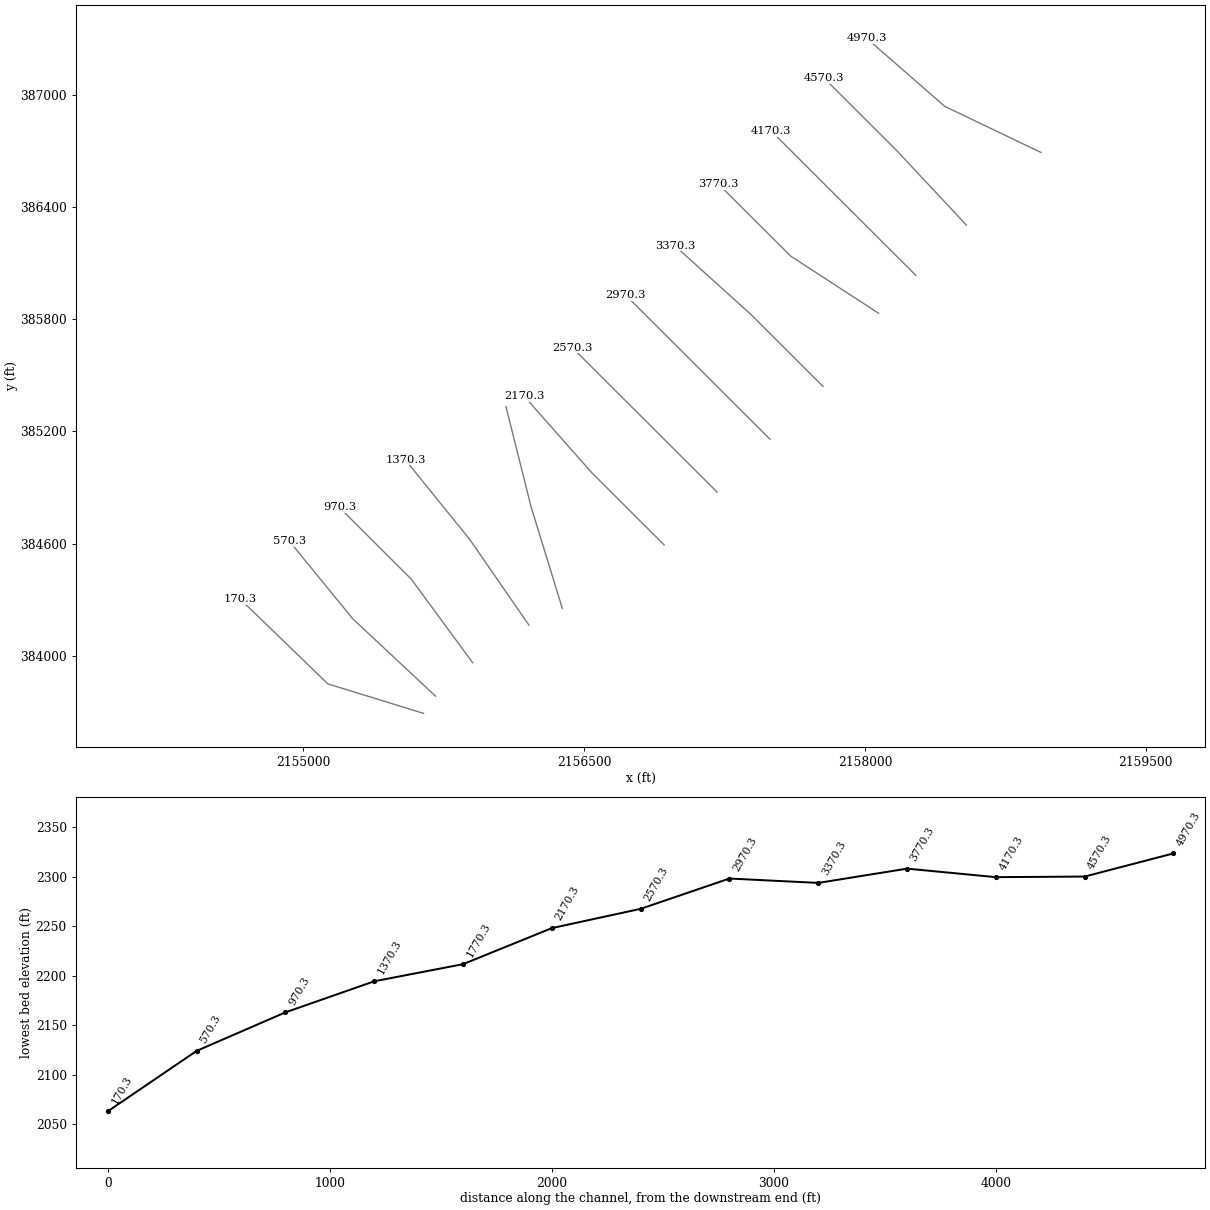
HEC-RAS study SpringCkT4.prj: SpringCkT4

--- SpringCkT4.g01 (geometry) --- (continued)

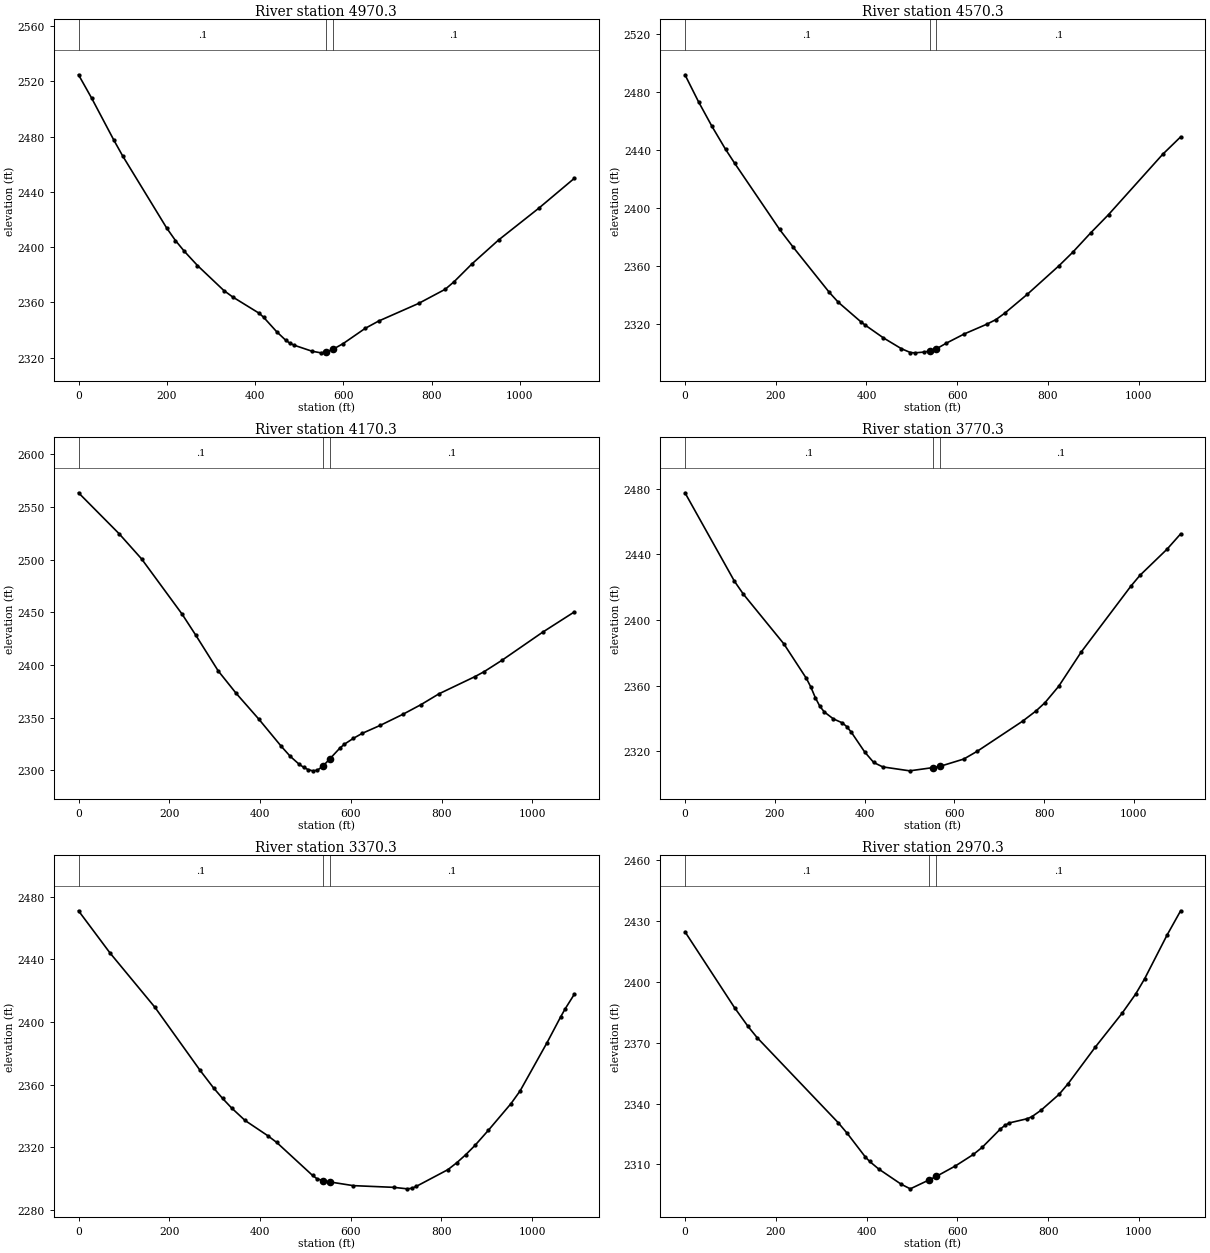
Type RM Length L Ch R = 1 ,4970.3  ,410.5,400,393.3
XS GIS Cut Line= 3
     2158939.912      386693.723     2158426.803      386940.086
     2158009.537      387304.414
#Sta/Elev= 30
       0 2524.76      30 2507.71    79.9 2477.53    99.9 2466.07   199.7 2413.82
   219.7  2404.7   239.7 2396.96   269.6 2386.61   329.5 2368.46   349.5 2363.82
   409.4 2352.03   419.4 2349.15   449.4 2338.54   469.3 2332.58   479.3 2330.28
   489.3 2328.83   529.2 2324.54   549.2 2323.38   561.7 2324.03   576.7 2325.98
   599.4 2330.02   649.8 2341.15     680 2346.39   770.6 2359.16     831 2369.43
   851.2 2374.94   891.5  2387.8   951.9 2405.13  1042.6 2428.04  1123.1 2449.67
#Mann= 3 , 0 , 0
       0      .1       0   561.7    .045       0   576.7      .1       0
Bank Sta=561.7,576.7
XS Rating Curve= 0 ,0
Exp/Cntr=0.3,0.1

Type RM Length L Ch R = 1 ,4570.3  ,399.2,400,400
XS GIS Cut Line= 3
     2158541.675      386305.187     2158168.828      386704.598
     2157782.797       387090.63
#Sta/Elev= 30
       0 2492.01    29.8  2473.4    59.6 2456.32    89.4 2440.55   109.3 2431.01
   208.6 2385.17   238.4 2372.98   317.9 2341.81   337.8 2334.95   387.4 2321.49
   397.4 2319.08   437.1 2310.36   476.8 2302.87   496.7 2300.21   506.6 2299.99
   526.5 2300.51   538.9 2301.24   553.9 2302.73   576.2 2306.71   615.9  2313.1
   665.5 2319.81   685.4 2322.98   705.2 2327.49   754.8 2340.52   824.3 2360.16
   854.1 2369.31   893.8 2382.73   933.5 2395.48  1052.6 2437.04  1092.3 2449.12
#Mann= 3 , 0 , 0
       0      .1       0   538.9    .045       0   553.9      .1       0
Bank Sta=538.9,553.9
XS Rating Curve= 0 ,0
Exp/Cntr=0.3,0.1

Type RM Length L Ch R = 1 ,4170.3  ,395.3,400,400
XS GIS Cut Line= 3
     2158272.066      386035.675     2157885.985      386421.756
     2157499.905      386807.836
#Sta/Elev= 30
       0  2563.5    89.4 2524.63     139 2500.68   228.3 2448.18   258.1 2428.41
   307.8  2394.3   347.4 2372.97   397.1 2348.57   446.7 2322.68   466.6 2313.12
   486.4 2305.52   496.4 2302.66   506.3 2300.46   516.2 2299.39   526.2 2299.98
   538.5 2303.88   553.5 2310.68   575.8 2320.99   585.7 2324.66   605.6 2330.26
   625.4 2335.07   665.1 2342.64   714.8 2353.12   754.5 2362.27   794.2 2372.55
   873.6 2388.92   893.4 2393.53   933.2 2404.48  1022.5 2431.06    1092 2450.23
#Mann= 3 , 0 , 0
       0      .1       0   538.5    .045       0   553.5      .1       0
Bank Sta=538.5,553.5
XS Rating Curve= 0 ,0
Exp/Cntr=0.3,0.1

Type RM Length L Ch R = 1 ,3770.3  ,404.7,400,401.1
XS GIS Cut Line= 3
     2158072.838      385832.884     2157603.143      386138.913
     2157218.884      386523.172
#Sta/Elev= 30
       0 2477.47   110.1 2423.59   130.1 2415.66   220.2  2385.4   270.3 2364.39
   280.3 2359.09   290.3 2352.59   300.3 2347.39   310.3 2343.88   330.4 2339.68
   350.4 2337.23   360.4 2334.94   370.4 2331.58   400.4 2319.44   420.4 2313.08
   440.5 2310.39   500.5 2307.99   553.1 2309.99   568.1 2310.74     621 2315.18
   651.2 2319.96   751.8 2338.22     782 2344.52   802.1 2349.61   832.3 2359.49
   882.6 2380.44   993.3  2420.6  1013.4 2427.15  1073.8 2443.11    1104 2452.42
#Mann= 3 , 0 , 0
       0      .1       0   553.1    .045       0   568.1      .1       0
Bank Sta=553.1,568.1
XS Rating Curve= 0 ,0
Exp/Cntr=0.3,0.1

Type RM Length L Ch R = 1 ,3370.3  ,400,400,398.9
XS GIS Cut Line= 3
     2157775.874      385441.264     2157389.896      385827.243
     2156984.506      386194.217
#Sta/Elev= 30
       0 2471.02    69.5 2444.07   168.7 2409.34     268  2369.2   297.7 2357.99
   317.6 2351.29   337.4 2345.22   367.2 2337.21   416.8 2327.58   436.7 2323.26
   516.1 2302.11     526 2299.99   538.4 2298.85   553.4 2298.02   605.5 2295.64
     695 2294.54   724.8 2293.59   734.8 2293.95   744.7 2295.17   814.3 2305.83
   834.2 2310.31   854.1 2315.49     874 2321.29   903.8 2331.03   953.5    2348
   973.4 2356.04    1033 2386.92  1062.8 2403.26  1072.8 2408.42  1092.7 2417.61
#Mann= 3 , 0 , 0
       0      .1       0   538.4    .045       0   553.4      .1       0
Bank Sta=538.4,553.4
XS Rating Curve= 0 ,0
Exp/Cntr=0.3,0.1

Type RM Length L Ch R = 1 ,2970.3  ,400,400,400
XS GIS Cut Line= 3
     2157493.134       385158.32     2157107.053        385544.4
     2156720.973       385930.48
#Sta/Elev= 30
       0 2424.71   109.2 2387.29     139 2378.03   158.8 2372.57   337.5 2330.63
   357.4 2325.37   397.1 2313.78     407 2311.48   426.9 2307.76   476.5 2300.25
   496.4    2298   538.5 2302.47   553.5 2304.09   595.6 2309.26   635.4 2314.95
   655.2 2318.54   694.9  2327.5   704.8 2329.27   714.8  2330.5   754.5 2332.59
   764.4 2333.58   784.2 2336.69     824 2344.52   843.8 2349.74   903.4 2367.69
     963 2384.54   992.7 2393.94  1012.6  2401.5  1062.2 2423.12    1092 2435.05
#Mann= 3 , 0 , 0
       0      .1       0   538.5    .045       0   553.5      .1       0
Bank Sta=538.5,553.5
XS Rating Curve= 0 ,0
Exp/Cntr=0.3,0.1

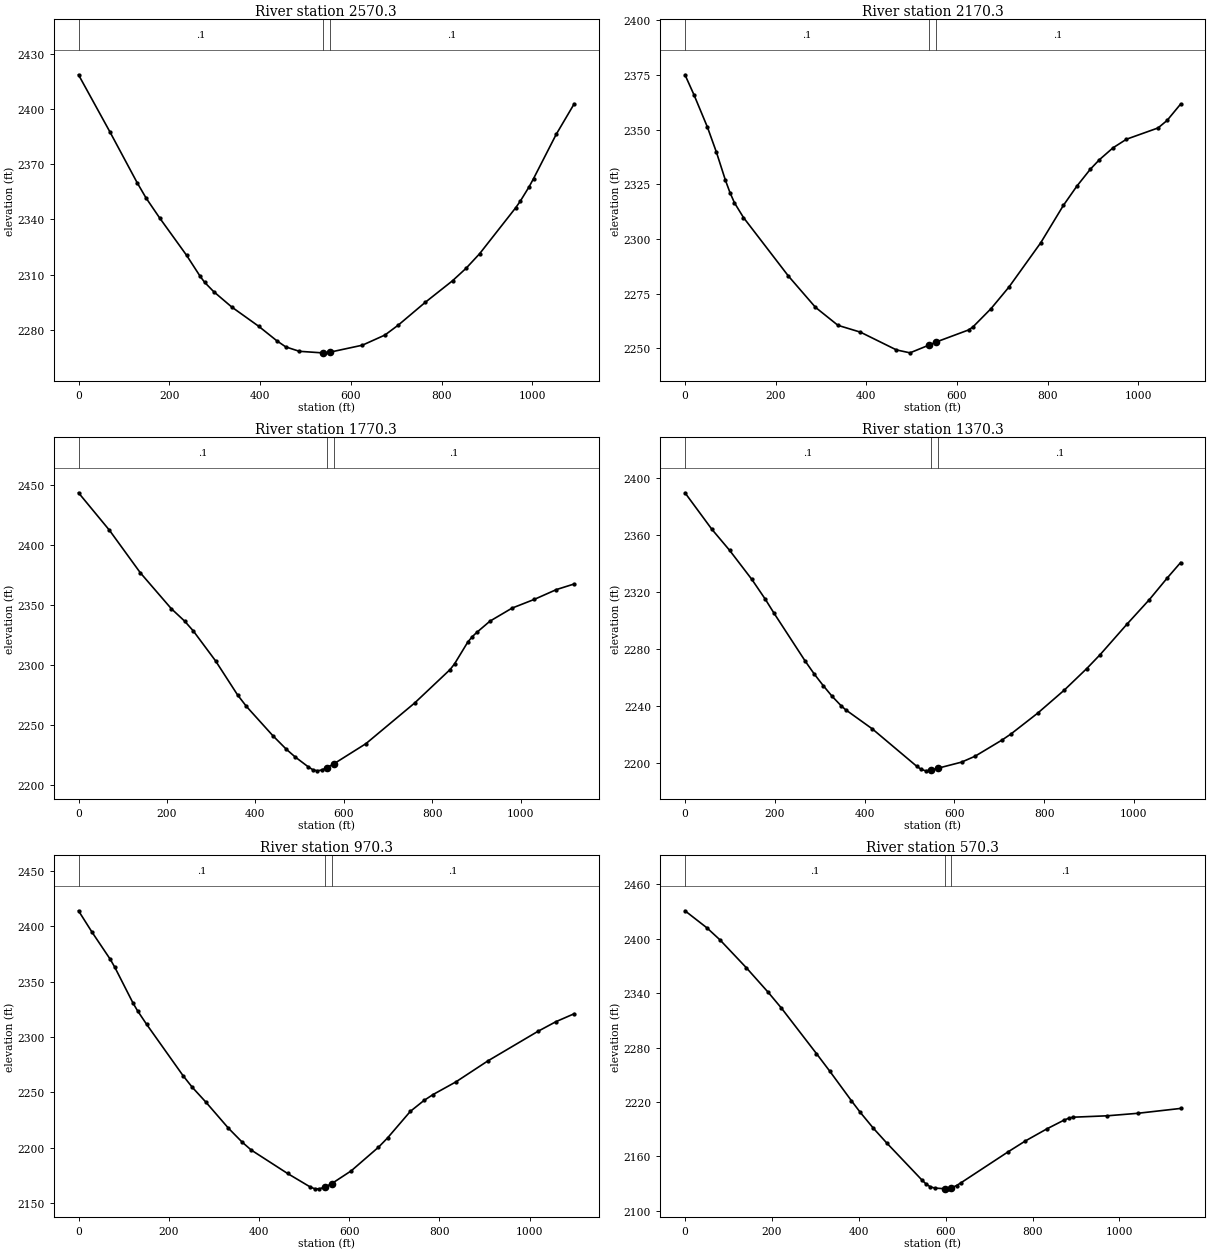
Type RM Length L Ch R = 1 ,2570.3  ,400,400,398.6
XS GIS Cut Line= 3
     2157210.291      384875.477     2156824.211      385261.557
      2156438.13      385647.637
#Sta/Elev= 30
       0 2418.66    69.5 2387.45     129 2360.04   148.9  2351.6   178.7  2340.8
   238.2 2320.42     268 2309.02     278 2305.72   297.8  2300.7   337.5 2292.34
   397.1 2281.83   436.8 2273.99   456.6 2270.63   486.4 2268.24   536.1  2267.4
   538.5 2267.44   553.5 2267.74   625.4 2271.56     675 2277.07   704.8 2282.55
   764.4 2294.97     824 2306.61   853.8 2313.38   883.5 2321.26     963 2346.27
   972.9 2349.76   992.7 2357.71  1002.6 2362.23  1052.3  2386.2    1092 2402.84
#Mann= 3 , 0 , 0
       0      .1       0   538.5    .045       0   553.5      .1       0
Bank Sta=538.5,553.5
XS Rating Curve= 0 ,0
Exp/Cntr=0.3,0.1

Type RM Length L Ch R = 1 ,2170.3  ,411.7,400,388.4
XS GIS Cut Line= 3
     2156927.286      384592.796     2156541.368      384978.714
      2156179.33      385389.161
#Sta/Elev= 30
       0 2375.02    19.8 2365.89    49.6 2351.04    69.5 2339.54    89.3 2326.76
    99.2  2321.2   109.2 2316.47     129 2309.78   228.2    2283   287.8 2268.73
   337.4  2260.5     387 2257.38   466.4 2249.26   496.2 2247.93   538.3 2251.48
   553.3 2252.83   625.4 2258.39   635.3 2259.82   675.1 2268.17   714.9 2278.11
   784.6 2298.25   834.4 2315.28   864.2 2324.11     894 2331.87     914 2336.21
   943.8 2341.61   973.7 2345.57  1043.3 2350.72  1063.2 2354.14  1093.1 2361.64
#Mann= 3 , 0 , 0
       0      .1       0   538.3    .045       0   553.3      .1       0
Bank Sta=538.3,553.3
XS Rating Curve= 0 ,0
Exp/Cntr=0.3,0.1

Type RM Length L Ch R = 1 ,1770.3  ,392.4,400,410.6
XS GIS Cut Line= 3
     2156383.553      384252.558     2156216.535      384797.245
     2156082.711      385331.837
#Sta/Elev= 30
       0  2443.3      70 2412.04   139.9 2376.55   209.9 2346.66   239.9 2336.35
   259.9 2327.99   309.8 2303.25   359.8 2274.72   379.8 2265.18   439.8 2240.68
   469.8 2229.56   489.8 2223.12   519.7  2214.8   529.7 2212.48   539.7 2211.52
   549.7 2212.18   562.2  2214.3   577.2 2217.32   649.9 2234.17   760.1 2268.07
   840.2 2295.93   850.3 2300.69   880.3 2318.89   890.4 2323.35   900.4 2326.86
   930.4  2336.3   980.5 2347.19  1030.6 2354.43  1080.7 2362.62  1120.8 2367.28
#Mann= 3 , 0 , 0
       0      .1       0   562.2    .045       0   577.2      .1       0
Bank Sta=562.2,577.2
XS Rating Curve= 0 ,0
Exp/Cntr=0.3,0.1

Type RM Length L Ch R = 1 ,1370.3  ,399.3,400,402.4
XS GIS Cut Line= 3
     2156204.957      384163.599     2155889.199      384621.818
     2155545.014      385047.958
#Sta/Elev= 30
       0 2389.59    59.6 2364.07    99.4 2349.16   149.1 2328.67   178.9 2314.82
   198.7 2304.82   268.3  2271.1   288.2 2262.16     308  2254.1   327.9 2246.54
   347.8 2239.98   357.7 2237.18   417.4 2223.68   516.7 2197.32   526.7 2195.18
   536.6 2194.22     549 2194.78     564 2196.09   616.2 2200.35   646.1 2204.46
   705.9 2215.79   725.8 2220.02   785.6 2234.71   845.3 2251.02   895.1  2266.1
     925  2275.9   984.7 2297.29  1034.5 2314.51  1074.4 2329.74  1104.2 2340.58
#Mann= 3 , 0 , 0
       0      .1       0     549    .045       0     564      .1       0
Bank Sta=549,564
XS Rating Curve= 0 ,0
Exp/Cntr=0.3,0.1

Type RM Length L Ch R = 1 ,970.3   ,396.1,400,397.4
XS GIS Cut Line= 3
     2155904.843      383961.789     2155577.529      384408.571
     2155192.428      384793.672
#Sta/Elev= 30
       0 2414.01    30.2 2394.55    70.5 2370.09    80.6 2362.87   120.8 2330.66
   130.9 2323.62     151 2311.41   231.6 2265.13   251.8 2254.74     282 2241.31
   332.3 2217.61   362.5 2205.12   382.7 2197.92   463.2 2176.76   513.6 2164.52
   523.6  2162.9   533.7 2162.85   546.3 2164.49   561.3 2167.61   604.3 2179.08
   664.8 2200.44     685 2208.86   735.4 2232.82   765.6 2242.66   785.8 2248.03
   836.2  2259.4   906.8  2278.3  1017.8 2305.02  1058.1 2313.84  1098.5    2321
#Mann= 3 , 0 , 0
       0      .1       0   546.3    .045       0   561.3      .1       0
Bank Sta=546.3,561.3
XS Rating Curve= 0 ,0
Exp/Cntr=0.3,0.1

Type RM Length L Ch R = 1 ,570.3   ,389.9,400,395.4
XS GIS Cut Line= 3
     2155706.577      383783.029     2155264.765      384196.535
     2154926.349       384611.63
#Sta/Elev= 30
       0 2430.98    50.4 2412.18    80.7 2398.78   141.2 2368.08   191.6 2340.93
   221.9 2323.55   302.6 2273.27   332.8 2254.14   383.2 2221.13   403.4 2208.39
   433.7 2190.78   463.9  2174.8   544.6 2134.04   554.7 2129.36   564.8 2126.09
   574.9  2124.8   597.6 2124.05   605.1 2123.94   612.6 2124.91     625  2127.6
   634.9 2130.53     744  2164.9   783.6 2176.88   833.2 2190.24   872.9 2199.96
   882.8 2201.82   892.8 2203.04   972.1  2204.6  1041.5 2207.33  1140.7 2212.73
#Mann= 3 , 0 , 0
       0      .1       0   597.6    .045       0   612.6      .1       0
Bank Sta=597.6,612.6
XS Rating Curve= 0 ,0
Exp/Cntr=0.3,0.1

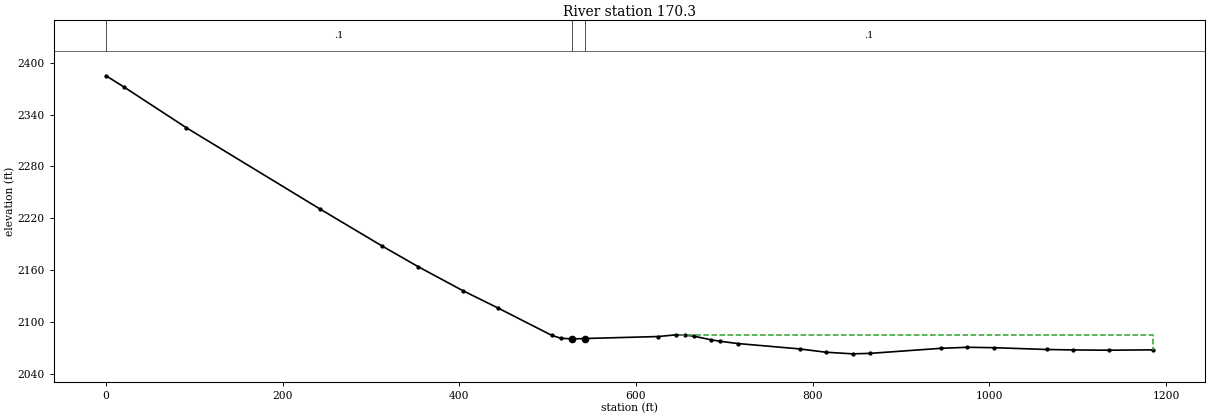
Type RM Length L Ch R = 1 ,170.3   ,196.1,170.3,155.9
XS GIS Cut Line= 3
     2155642.349      383690.954     2155131.152      383848.838
     2154664.143      384301.415
#Sta/Elev= 30
       0 2385.05    20.2 2372.11    90.8 2324.94   242.3 2230.68   312.9 2187.64
   353.3 2163.97   403.8 2136.21   444.2 2115.83   504.7 2084.32   514.8 2081.07
   527.5 2080.22   542.5 2080.72   625.1 2083.01   645.1 2084.96   655.1 2084.67
   665.1 2083.53   685.1  2079.2   695.1 2077.53   715.1  2074.9   785.2 2068.67
   815.2  2064.8   845.2 2062.96   865.2 2063.51   945.2 2069.36   975.2 2070.54
  1005.3 2070.08  1065.3 2067.99  1095.3 2067.46  1135.3 2067.16  1185.4 2067.57
#Mann= 3 , 0 , 0
       0      .1       0   527.5    .045       0   542.5      .1       0
#XS Ineff= 2 , 0
                          648.36         2085.09
Permanent Ineff=
       F       F
Bank Sta=527.5,542.5
XS Rating Curve= 0 ,0
Exp/Cntr=0.3,0.1

Chan Stop Cuts=-1
Use User Specified Reach Order=0